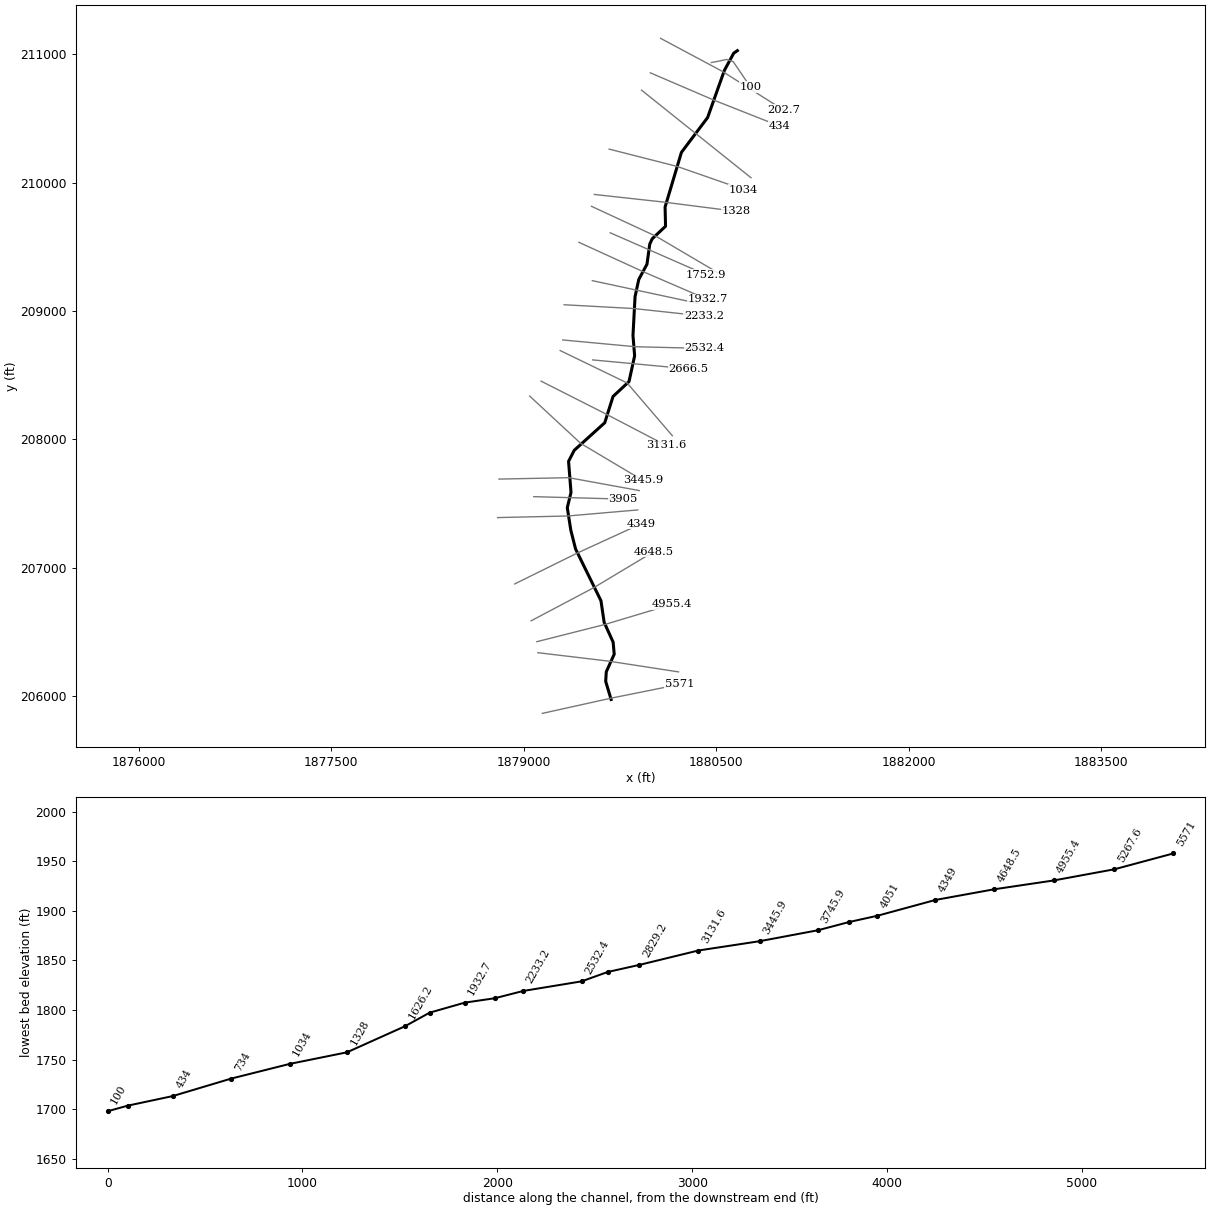
--- BtrBrnch.prj (project) ---

Proj Title=BtrBrnch
Current Plan=p01
Default Exp/Contr=0,0
English Units
Geom File=g01
Flow File=f01
Plan File=p01
BEGIN DESCRIPTION:
END DESCRIPTION:
DSS Export Rating Curves= 0
DSS Export Rating Curve Sorted= 0
DSS Export Volume Flow Curves= 0
DXF OffsetX= 0
DXF OffsetY= 0
DXF ScaleX= 0
DXF ScaleY= 0

--- BtrBrnch.p01 (plan) ---

Plan Title=Floodplain
Program Version=4.00
Geom File=g01
Flow File=f01
K Sum by GR=0
Std Step Tol=0.01
Critical Tol=0.01
Num of Std Step Trials=20
Max Error Tol=0.3
Flow Tol Ratio=0.001
Split Flow NTrial=30
Split Flow Tol=0.02
Split Flow Ratio=0.02
Log Output Level=0
Friction Slope Method=1
Unsteady Friction Slope Method=2
Unsteady Bridges Friction Slope Method=1
Global Log Level=0
CheckData=False
Run HTab=0
Run UNet=0
Run PostProcess=0
UNET Theta=0
UNET Theta Warmup=0
UNET ZTol=0
UNET ZSATol=0
UNET MxIter=0
UNET MaxInSteps=0
UNET DtIC=0
UNET DtMin=0
UNET MaxCRTS=0
UNET WFStab=0
UNET SFStab=0
UNET WFX=0
UNET SFX=0
UNET DSS MLevel=0
UNET DZMax Abort=0
UNET Convert EG Bridges=0
UNET Use Existing IB Tables=0
UNET Froude Limit=0
UNET Froude Power=0
Write IC File=0
Echo Input=False
Echo Output=False
Write Detailed=0

--- BtrBrnch.f01 (steady flow) ---

Flow Title=NFF Regression Equation
Program Version=4.00
Number of Profiles=1
Profile Names=P100yr
River Rch & RM=BtrBrnch,Main      ,5571
897.6510
River Rch & RM=BtrBrnch,Main      ,3445.9
976.4719
River Rch & RM=BtrBrnch,Main      ,2666.5
1057.838
River Rch & RM=BtrBrnch,Main      ,202.7
1112.224
Boundary for River Rch & Prof#=BtrBrnch,Main      ,1
Up Type=0
Dn Type=3
Dn Slope=0.051675

--- BtrBrnch.g01 (geometry) ---

Geom Title=USGS 3m DEM
Program Version=4.10

River Reach=BtrBrnch        ,Main
Reach XY= 30
     1879681.231       205973.87     1879639.154      206114.816
     1879643.706      206189.463     1879705.539      206326.492
     1879697.038       206420.57     1879627.224      206574.459
     1879602.225      206742.935      1879404.51      207146.298
     1879367.563      207291.666     1879339.966      207467.838
     1879369.002       207587.11     1879349.833      207828.847
     1879394.125      207914.815     1879631.854      208129.577
      1879696.34      208334.229     1879820.783      208450.094
     1879864.562      208650.989     1879851.686        208809.3
     1879867.907      209112.813     1879896.976      209246.018
     1879960.808      209364.549     1879982.352      209520.973
     1880001.446      209562.342     1880105.406      209660.226
     1880101.847      209810.048     1880229.176      210235.956
     1880432.885      210506.548     1880563.996       210874.85
     1880636.497      211008.564     1880664.787      211027.843

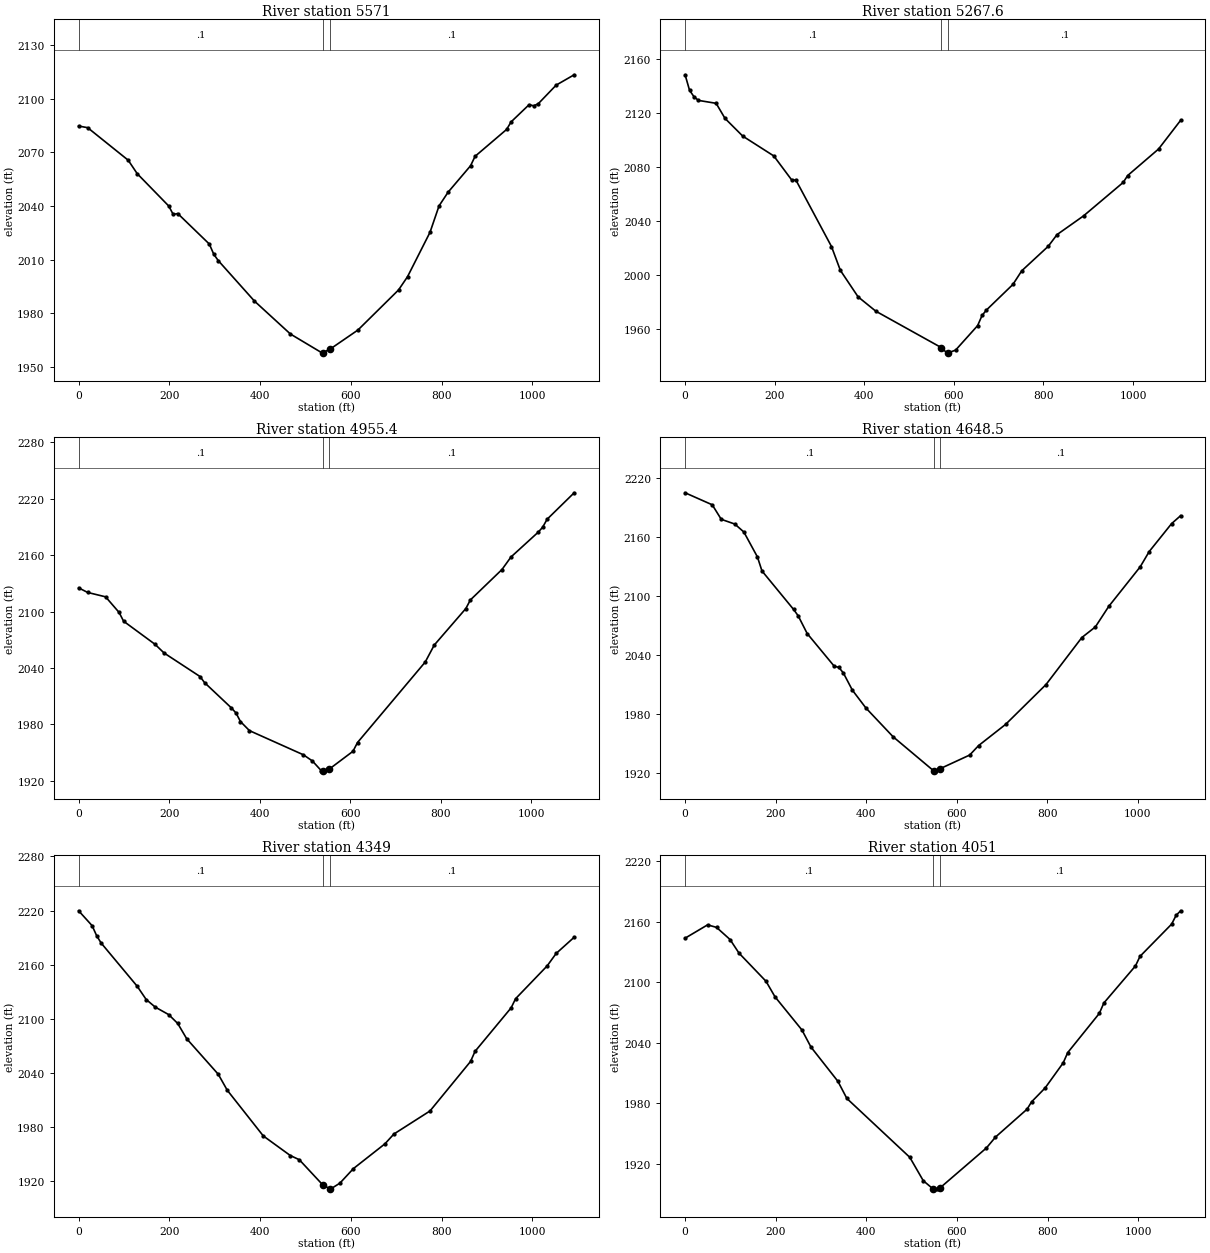
Type RM Length L Ch R = 1 ,5571    ,311.8,303.3,295.3
XS GIS Cut Line= 3
     1879146.062      205865.538     1879679.261      205983.674
     1880214.536      206091.247
#Sta/Elev= 30
       0 2084.65    19.9 2083.74   109.2 2065.58   129.1 2058.06   198.6 2039.99
   208.5 2035.26   218.4  2035.8     288 2018.76   297.9 2013.01   307.8 2009.49
   387.3 1986.95   466.7 1968.52   536.2    1958   538.6 1958.18   553.6 1959.97
   615.6 1970.75     705 1993.11   724.8  2000.5   774.4 2025.32   794.3 2040.07
   814.2  2047.7   863.8 2062.49   873.7 2067.74   943.2 2082.76   953.1 2086.97
   992.8 2096.59  1002.8 2095.96  1012.7 2097.04  1052.4  2107.5  1092.1 2113.28
#Mann= 3 , 0 , 0
       0      .1       0   538.6    .045       0   553.6      .1       0
Bank Sta=538.6,553.6
XS Rating Curve= 0 ,0
Exp/Cntr=0.3,0.1

Type RM Length L Ch R = 1 ,5267.6  ,302.6,311.7,321.6
XS GIS Cut Line= 3
     1879110.845      206338.325     1879661.462      206272.633
     1880206.654      206188.629
#Sta/Elev= 30
       0 2148.48     9.9 2136.99    19.8 2132.19    29.7 2129.46    69.3 2127.28
    89.1 2116.08   128.7 2102.93     198  2088.2   237.6 2070.52   247.6 2070.14
   326.8 2020.93   346.6 2003.23   386.2 1983.55   425.8  1972.9   572.3  1945.8
   584.1 1941.98   587.3 1942.01   603.8 1943.98     653 1962.19   662.9 1969.73
   672.7 1973.78   731.8 1992.78   751.5  2002.9   810.6 2021.09   830.3 2029.78
   889.4 2043.67   978.1 2068.57   987.9 2073.63  1056.9 2093.34  1106.2 2114.66
#Mann= 3 , 0 , 0
       0      .1       0   572.3    .045       0   587.3      .1       0
Bank Sta=572.3,587.3
XS Rating Curve= 0 ,0
Exp/Cntr=0.3,0.1

Type RM Length L Ch R = 1 ,4955.4  ,301.1,306.8,312.4
XS GIS Cut Line= 3
     1879102.869      206423.966     1879632.366      206558.001
     1880157.678      206715.465
#Sta/Elev= 30
       0  2125.3    19.9 2120.43    59.6 2115.75    89.4 2099.15    99.3 2089.84
   168.8 2065.25   188.7 2056.04   268.1 2031.01   278.1 2024.55   337.6 1997.54
   347.6 1992.23   357.5 1983.08   377.4 1973.44   496.5 1947.76   516.4 1941.19
   536.3  1930.7   538.7 1930.74   553.7 1932.58     606 1951.49     616  1960.8
   765.6 2046.42   785.5 2064.44   855.3  2103.3   865.3 2112.44   935.1 2144.79
     955 2158.11  1014.8 2184.36  1024.8 2189.64  1034.8 2198.26  1094.6 2226.42
#Mann= 3 , 0 , 0
       0      .1       0   538.7    .045       0   553.7      .1       0
Bank Sta=538.7,553.7
XS Rating Curve= 0 ,0
Exp/Cntr=0.3,0.1

Type RM Length L Ch R = 1 ,4648.5  ,300.6,299.5,297.1
XS GIS Cut Line= 3
      1879058.02      206586.469     1879543.798      206843.401
     1880011.708       207124.07
#Sta/Elev= 30
       0 2204.47      60 2192.24    79.9  2177.5   109.9 2172.67   129.9 2164.57
   159.9  2139.2   169.9 2124.99   239.8 2085.85   249.8 2079.48   269.8 2061.38
   329.7 2028.07   339.7 2027.02   349.7 2021.32   369.7 2003.79   399.7 1985.61
   459.6 1956.45   549.2 1921.84   549.5 1921.76   564.2 1924.07   628.9  1937.8
   648.8  1947.5   708.3 1968.97   797.6 2009.47   876.9 2057.31   906.7 2068.07
   936.4 2089.01  1005.9 2129.22  1025.7  2144.7  1075.3 2173.15  1095.2  2181.2
#Mann= 3 , 0 , 0
       0      .1       0   549.2    .045       0   564.2      .1       0
Bank Sta=549.2,564.2
XS Rating Curve= 0 ,0
Exp/Cntr=0.3,0.1

Type RM Length L Ch R = 1 ,4349    ,307.2,297.9,290.2
XS GIS Cut Line= 3
     1878930.191      206873.749     1879419.816      207115.269
     1879916.367      207342.959
#Sta/Elev= 30
       0 2219.74    29.8 2203.16    39.7 2192.07    49.6 2183.95     129 2136.02
   148.9 2121.25   168.8 2112.84   198.5 2104.48   218.4 2094.66   238.2 2077.68
   307.7 2038.29   327.6 2020.52     407  1969.8   466.5 1948.06   486.4 1943.38
   538.5 1915.21   553.5  1911.3   555.9 1911.07   575.8 1917.36   605.6 1933.52
   675.1 1961.03   694.9 1971.93   774.4  1997.5   863.8 2052.47   873.7 2063.67
   953.2 2111.98   963.1 2122.15  1032.6 2158.52  1052.5 2172.37  1092.2 2190.35
#Mann= 3 , 0 , 0
       0      .1       0   538.5    .045       0   553.5      .1       0
Bank Sta=538.5,553.5
XS Rating Curve= 0 ,0
Exp/Cntr=0.3,0.1

Type RM Length L Ch R = 1 ,4051    ,147.4,145.8,143.3
XS GIS Cut Line= 3
     1878797.013      207390.698     1879342.468      207403.069
     1879888.719      207450.334
#Sta/Elev= 30
       0  2143.8    49.6 2157.01    69.4 2154.52    99.2 2142.49     119 2128.99
   178.6 2101.06   198.4 2085.68   257.9 2052.74   277.8 2035.82   337.3 2001.81
   357.1 1984.78     496  1926.4   525.8 1903.16   546.9 1895.22   555.6 1895.12
   561.9 1895.73   665.2 1935.69   685.2 1946.47   754.9 1974.16   764.9 1981.45
   794.8 1995.23   834.7 2020.14   844.7 2030.31   914.4  2069.2   924.4 2079.51
   994.2 2116.29  1004.2 2125.78    1074 2157.74  1083.9 2166.46  1093.9 2170.99
#Mann= 3 , 0 , 0
       0      .1       0   546.9    .045       0   561.9      .1       0
Bank Sta=546.9,561.9
XS Rating Curve= 0 ,0
Exp/Cntr=0.3,0.1

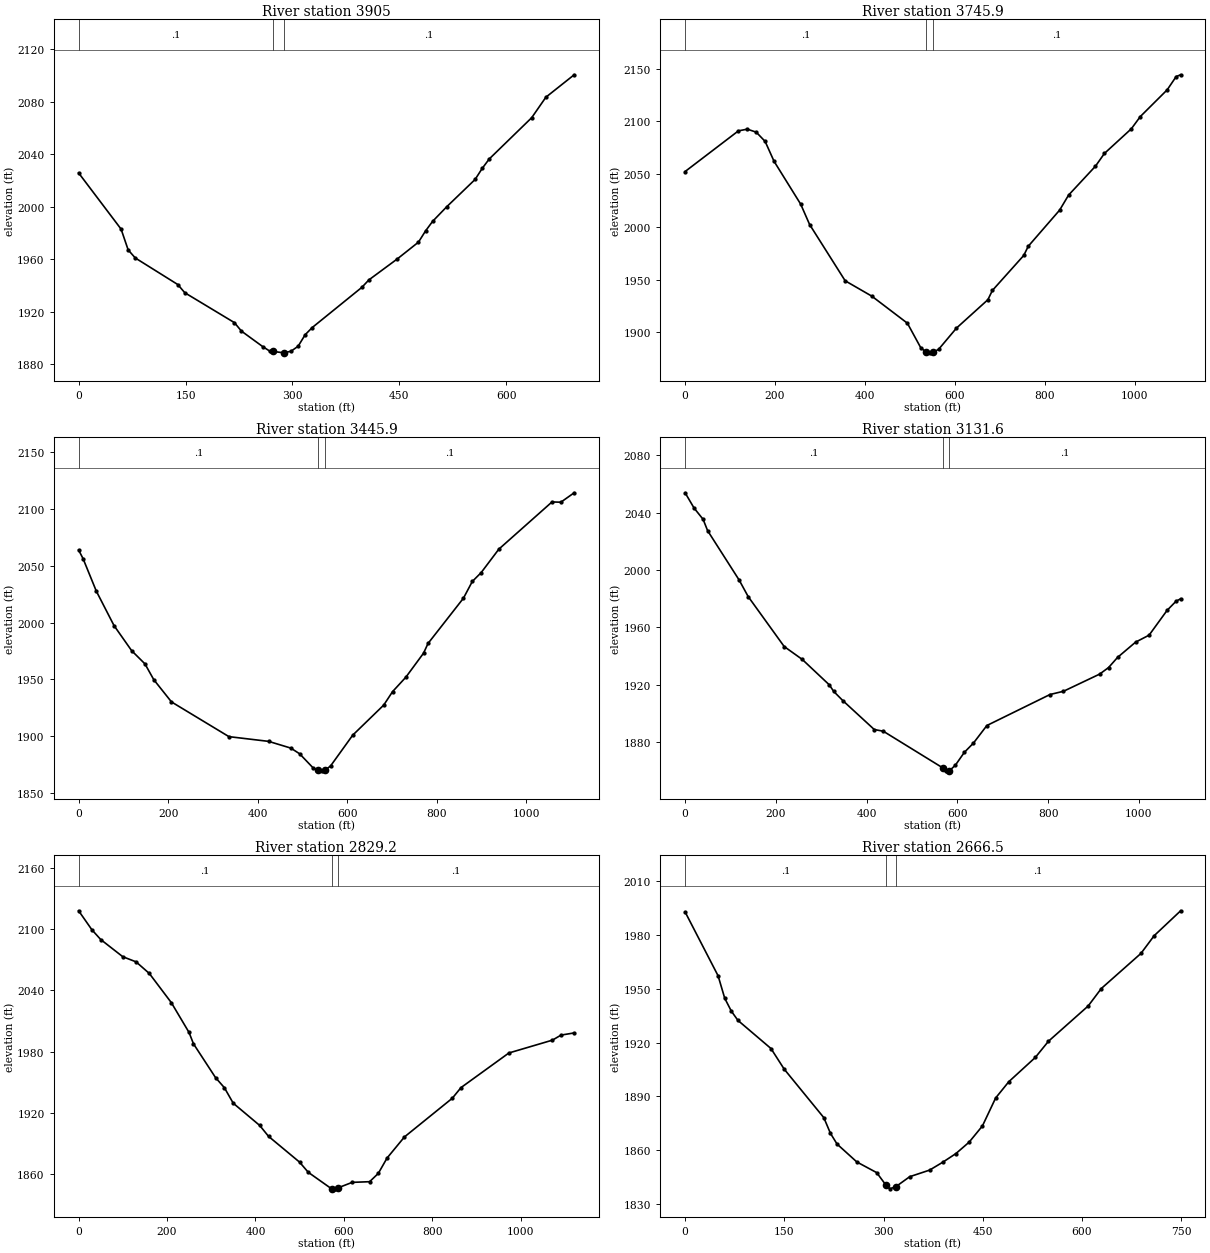
Type RM Length L Ch R = 1 ,3905    ,158.2,159.2,155.6
XS GIS Cut Line= 2
     1879078.878      207553.779      1879774.06      207534.658
#Sta/Elev= 30
       0 2025.75    59.6 1982.97    69.5 1967.16    79.5 1961.01   139.1  1940.8
     149 1934.54   218.6 1911.78   228.5 1905.32   258.3 1893.54   268.2  1890.1
   272.7 1889.86   287.7 1888.81   288.1 1888.78     298    1890     308 1893.78
   317.9 1902.57   327.8 1908.03   397.4 1938.62   407.3 1944.31   447.1 1960.25
   476.9 1973.07   486.8 1981.58   496.8 1988.92   516.6 2000.04   556.4 2020.82
   566.3 2029.17   576.2 2036.39   635.8 2067.83   655.7 2083.42   695.4  2100.5
#Mann= 3 , 0 , 0
       0      .1       0   272.7    .045       0   287.7      .1       0
Bank Sta=272.7,287.7
XS Rating Curve= 0 ,0
Exp/Cntr=0.3,0.1

Type RM Length L Ch R = 1 ,3745.9  ,317.4,300,291.8
XS GIS Cut Line= 3
      1878807.82      207690.681      1879351.54       207701.53
     1879900.752      207601.159
#Sta/Elev= 30
       0 2052.51   118.6  2091.1   138.4  2092.7   158.2 2089.86     178 2081.08
   197.8 2062.25   257.1 2021.54   276.9 2002.26     356 1948.86   415.3 1934.27
   494.4 1908.62     524 1885.45   536.3 1881.14   543.8 1880.51   551.3 1881.04
   563.8 1883.82   603.6    1904   673.4 1930.91   683.4 1939.68   753.2 1972.92
   763.2 1981.62     833 2015.92   852.9 2030.16   912.7 2057.59   932.6 2069.68
   992.5 2093.08  1012.4 2104.65  1072.2 2130.03  1092.2 2142.63  1102.1  2144.3
#Mann= 3 , 0 , 0
       0      .1       0   536.3    .045       0   551.3      .1       0
Bank Sta=536.3,551.3
XS Rating Curve= 0 ,0
Exp/Cntr=0.3,0.1

Type RM Length L Ch R = 1 ,3445.9  ,308,314.2,315.7
XS GIS Cut Line= 3
     1879046.836      208337.365     1879444.987      207968.317
     1879929.328      207679.991
#Sta/Elev= 30
       0 2063.93     9.9 2056.38    39.5 2027.74      79 1997.42   118.4  1975.3
   148.1 1963.67   167.8 1949.76   207.3 1930.17   335.6 1899.57   424.4 1895.39
   473.8 1889.48   493.5 1884.47   523.1 1872.24   535.4 1869.81   542.9 1869.44
   550.4 1870.01   562.7 1873.79   612.1 1900.88   681.3 1927.36   701.1 1939.24
   730.8 1951.97   770.3 1973.15   780.2 1981.63   859.3 2021.52   879.1 2036.26
   898.9 2044.07   938.4 2064.74  1057.1 2106.33  1076.9  2106.1  1106.6  2114.4
#Mann= 3 , 0 , 0
       0      .1       0   535.4    .045       0   550.4      .1       0
Bank Sta=535.4,550.4
XS Rating Curve= 0 ,0
Exp/Cntr=0.3,0.1

Type RM Length L Ch R = 1 ,3131.6  ,300.8,302.5,293.9
XS GIS Cut Line= 3
     1879135.797      208453.553      1879622.92      208206.943
      1880107.08      207954.336
#Sta/Elev= 30
       0 2053.93    19.8 2043.27    39.7 2035.41    49.6 2027.52   119.1  1993.1
     139 1981.56   218.4 1946.72   258.1 1937.77   317.7 1920.04   327.6 1915.41
   347.4 1909.09   416.9 1888.86   436.8 1887.68   567.7 1862.16   575.8 1860.06
   582.7 1860.17   595.6 1863.97   615.5 1872.98   635.4 1879.38   665.1 1891.66
   804.2 1913.27   833.9 1915.53   913.4 1927.47   933.2 1932.05   953.1 1939.15
   992.8 1949.79  1022.6 1954.66  1062.3 1971.98  1082.2 1978.38  1092.1 1980.01
#Mann= 3 , 0 , 0
       0      .1       0   567.7    .045       0   582.7      .1       0
Bank Sta=567.7,582.7
XS Rating Curve= 0 ,0
Exp/Cntr=0.3,0.1

Type RM Length L Ch R = 1 ,2829.2  ,155.2,162.7,180.4
XS GIS Cut Line= 3
     1879284.344      208691.956     1879805.957      208439.539
     1880158.259       208028.46
#Sta/Elev= 30
       0 2118.15      30 2099.53      50 2089.95    99.9 2073.11   129.9 2068.09
   159.9  2056.7   209.8 2028.02   249.8 1998.83   259.8 1987.72   309.7 1954.59
   329.7  1944.7   349.7 1929.51   409.6  1907.7   429.6    1897   499.6  1871.8
   519.5 1861.74     572 1845.64   579.5 1845.56     587 1846.57   618.8 1851.91
   658.2 1852.56   677.9 1860.72   697.6 1875.72     737 1896.44   845.2 1934.36
   864.9  1944.8   973.2 1978.74  1071.6 1991.32  1091.3 1996.29  1120.9  1998.4
#Mann= 3 , 0 , 0
       0      .1       0     572    .045       0     587      .1       0
Bank Sta=572,587
XS Rating Curve= 0 ,0
Exp/Cntr=0.3,0.1

Type RM Length L Ch R = 1 ,2666.5  ,134.1,134.1,135.6
XS GIS Cut Line= 2
      1879537.78      208619.088     1880283.496      208549.433
#Sta/Elev= 30
       0 1993.01    49.9 1957.33    59.9 1944.81    69.9 1937.61    79.9 1932.44
   129.8 1916.75   149.8 1905.23   209.7 1878.14   219.7 1869.39   229.7  1863.4
   259.6 1853.41   289.6 1847.46   303.7 1840.43   309.6 1838.41   318.7 1839.66
   339.5 1845.19   369.5 1848.86   389.5 1853.28   409.4 1858.12   429.4 1864.51
   449.4 1873.52   469.4 1889.14   489.3 1898.23   529.3 1911.75   549.2  1920.8
   609.2 1940.48   629.1 1950.25     689 1969.84     709 1979.74     749 1993.65
#Mann= 3 , 0 , 0
       0      .1       0   303.7    .045       0   318.7      .1       0
Bank Sta=303.7,318.7
XS Rating Curve= 0 ,0
Exp/Cntr=0.3,0.1

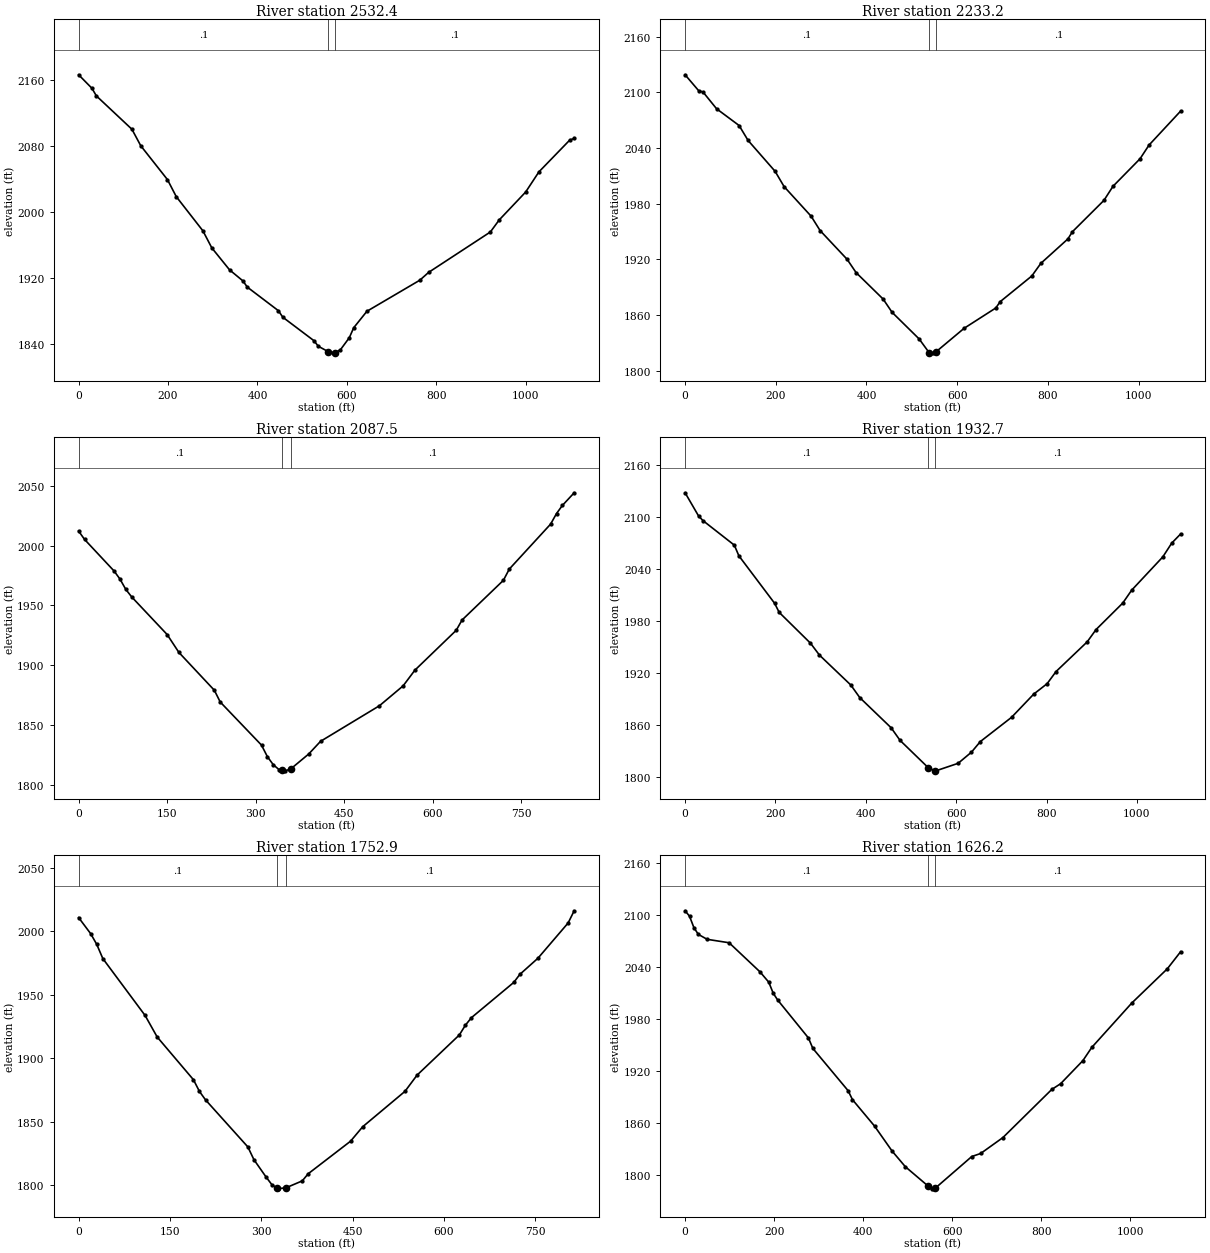
Type RM Length L Ch R = 1 ,2532.4  ,298.3,299.2,297.3
XS GIS Cut Line= 3
     1879304.625      208774.484     1879868.117      208721.836
     1880410.394      208708.239
#Sta/Elev= 30
       0 2166.82    29.8 2150.38    39.7 2141.15   119.2 2100.62     139 2080.55
   198.6  2039.5   218.4 2018.73     278 1977.17   297.9 1956.46   337.6 1929.76
   367.4 1916.39   377.3  1908.8   446.8 1880.16   456.7 1872.22   526.2 1843.75
   536.2 1836.89   558.4 1830.37   573.4 1828.94   585.7 1832.78   605.4  1847.3
   615.3 1859.44   644.8 1879.44   763.2 1917.22   782.9 1926.74     921 1975.82
   940.7 1990.42   999.9 2024.35  1029.5 2048.81  1098.5 2087.48  1108.4 2089.44
#Mann= 3 , 0 , 0
       0      .1       0   558.4    .045       0   573.4      .1       0
Bank Sta=558.4,573.4
XS Rating Curve= 0 ,0
Exp/Cntr=0.3,0.1

Type RM Length L Ch R = 1 ,2233.2  ,149.2,145.7,143.3
XS GIS Cut Line= 3
      1879315.69      209048.756     1879860.711      209019.004
     1880404.472      208960.016
#Sta/Elev= 30
       0  2118.8    29.8 2101.73    39.7 2100.14    69.5 2082.16   119.1 2064.15
   138.9 2048.08   198.5 2014.81   218.3 1998.35   277.9 1966.47   297.7 1951.01
   357.3 1920.02   377.1  1905.7   436.7 1877.21   456.5 1862.91   516.1 1834.26
   538.3 1819.39   545.8 1819.28   553.3 1820.36   615.4 1845.74   685.1 1867.58
     695 1874.46   764.6 1902.07   784.5 1915.65   844.2 1941.99   854.1 1949.71
   923.7 1983.53   943.6 1998.67  1003.3 2028.34  1023.2 2043.15  1092.8  2079.7
#Mann= 3 , 0 , 0
       0      .1       0   538.3    .045       0   553.3      .1       0
Bank Sta=538.3,553.3
XS Rating Curve= 0 ,0
Exp/Cntr=0.3,0.1

Type RM Length L Ch R = 1 ,2087.5  ,159.7,154.8,150.5
XS GIS Cut Line= 2
     1879535.048       209236.42     1880355.882      209060.235
#Sta/Elev= 30
       0  2012.1      10 2005.14      60 1978.78      70 1972.04      80 1963.34
      90 1957.06   149.9 1925.74   169.9 1910.76   229.9  1879.2   239.9 1869.38
   309.8  1833.4   319.8 1823.73   329.8    1817   339.8 1812.83   344.2 1812.43
   349.8 1811.93   359.2 1813.46   389.8 1825.99   409.8 1836.55   509.7 1866.31
   549.7 1882.86   569.7 1895.99   639.6 1929.21   649.6 1937.86   719.6 1970.98
   729.6 1980.36   799.6 2017.91   809.6 2026.73   819.5 2033.48   839.5 2044.06
#Mann= 3 , 0 , 0
       0      .1       0   344.2    .045       0   359.2      .1       0
Bank Sta=344.2,359.2
XS Rating Curve= 0 ,0
Exp/Cntr=0.3,0.1

Type RM Length L Ch R = 1 ,1932.7  ,179.7,180,179.6
XS GIS Cut Line= 3
     1879430.545       209535.07     1879926.363      209308.423
     1880432.741      209089.665
#Sta/Elev= 30
       0  2128.2    29.7 2101.56    39.6 2096.07     109 2067.78     119  2055.5
   198.2 2000.68   208.2 1990.28   277.5 1954.72   297.4 1940.95   366.8 1906.45
   386.6 1891.96     456 1857.17   475.8 1842.61   537.9 1811.25   552.9 1807.58
     555 1807.48   604.3 1816.15   633.8    1829   653.5 1841.26   722.5 1869.18
   771.7 1896.01   801.3 1908.02     821    1922   889.9  1956.2   909.6 1970.44
   968.7    2001   988.4 2015.85  1057.4 2054.28  1077.1 2070.15  1096.8  2080.7
#Mann= 3 , 0 , 0
       0      .1       0   537.9    .045       0   552.9      .1       0
Bank Sta=537.9,552.9
XS Rating Curve= 0 ,0
Exp/Cntr=0.3,0.1

Type RM Length L Ch R = 1 ,1752.9  ,125.7,126.5,124
XS GIS Cut Line= 2
     1879674.358      209609.278     1880420.074      209282.857
#Sta/Elev= 30
       0 2010.94    19.8 1998.26    29.8 1989.81    39.7 1978.71   109.2 1933.86
     129 1916.94   188.6 1883.28   198.5 1874.03   208.5 1867.39     278 1830.36
   287.9 1820.38   307.7 1806.82   317.7 1800.47   326.3 1797.78   327.6 1797.37
   341.3 1798.34   367.3 1803.62   377.2 1809.29   446.7 1834.89   466.6 1846.25
   536.1 1874.14   555.9 1886.88   625.4 1918.54   635.3  1926.2   645.3 1932.17
   714.8  1959.9   724.7 1966.19   754.5 1978.95   804.1 2006.72     814  2016.3
#Mann= 3 , 0 , 0
       0      .1       0   326.3    .045       0   341.3      .1       0
Bank Sta=326.3,341.3
XS Rating Curve= 0 ,0
Exp/Cntr=0.3,0.1

Type RM Length L Ch R = 1 ,1626.2  ,292,298.1,307.4
XS GIS Cut Line= 3
     1879528.322      209815.589     1880030.918       209582.32
     1880512.532      209298.523
#Sta/Elev= 30
       0 2104.49     9.9 2098.25    19.8 2085.02    29.7 2077.28    49.5 2071.56
    98.9 2067.59   168.2 2034.04     188 2022.07   197.9 2009.41   207.8 2001.63
     277  1957.8   286.9 1945.75   366.1 1896.97     376 1886.53   425.5 1856.12
     465 1827.24   494.7 1809.22   546.2 1786.74   554.1 1783.68   561.2 1784.11
   643.9 1820.95   663.9 1824.47   713.8  1842.8   823.6 1898.34   843.6 1905.01
   893.5 1931.58   913.5 1946.86  1003.3 1998.02  1083.2 2037.57  1113.1 2057.26
#Mann= 3 , 0 , 0
       0      .1       0   546.2    .045       0   561.2      .1       0
Bank Sta=546.2,561.2
XS Rating Curve= 0 ,0
Exp/Cntr=0.3,0.1

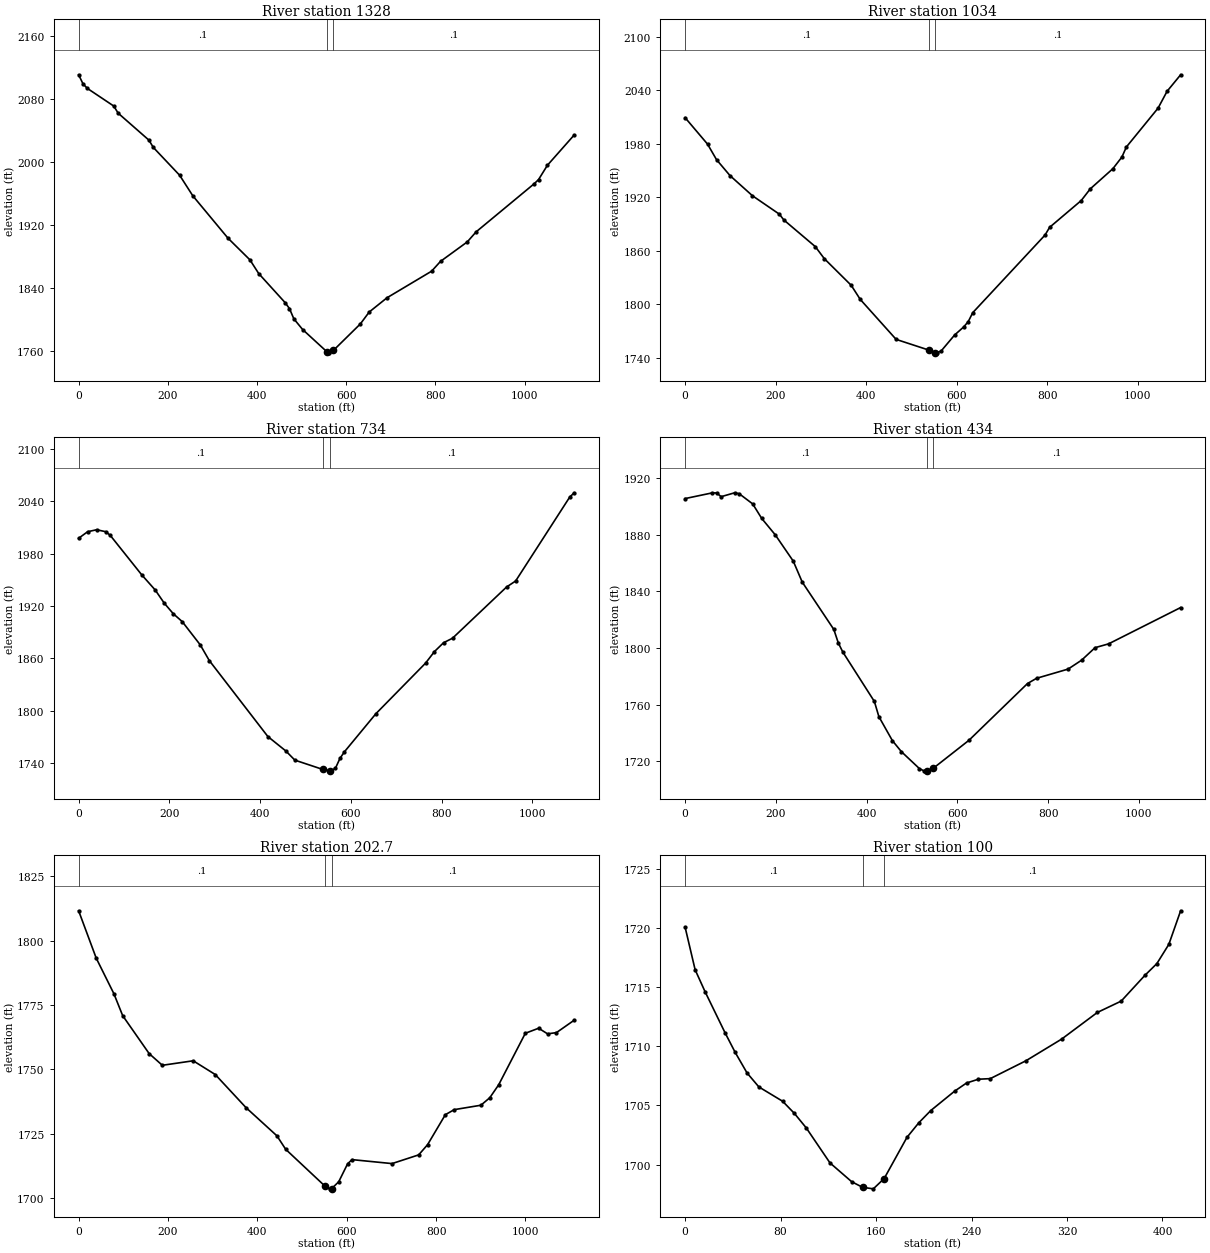
Type RM Length L Ch R = 1 ,1328    ,296.7,293.9,289.2
XS GIS Cut Line= 3
     1879550.469      209907.895     1880089.058      209848.695
     1880654.081      209776.613
#Sta/Elev= 30
       0 2110.17     9.8 2098.65    19.7 2092.83    78.8 2070.48    88.7 2061.43
   157.6 2027.27   167.5 2017.99   226.6 1982.63   256.1 1956.59     335 1902.84
   384.2 1875.35   403.9 1857.97     463 1821.14   472.9 1813.49   482.7  1800.5
   502.4 1786.96   556.4 1758.95   561.8 1757.37   571.4 1760.45   631.8 1794.03
   651.8  1809.2   691.7 1827.27   791.7 1860.99   811.6 1873.41   871.6  1898.1
   891.6 1910.93  1021.5 1971.81  1031.5  1977.2  1051.5 1995.44  1111.4 2033.75
#Mann= 3 , 0 , 0
       0      .1       0   556.4    .045       0   571.4      .1       0
Bank Sta=556.4,571.4
XS Rating Curve= 0 ,0
Exp/Cntr=0.3,0.1

Type RM Length L Ch R = 1 ,1034    ,309.6,300.1,292.4
XS GIS Cut Line= 3
     1879666.244      210261.087     1880194.983      210126.455
     1880713.585      209945.926
#Sta/Elev= 30
       0 2009.21    49.6 1979.54    69.4 1962.17    99.2 1944.28   148.8 1921.71
   208.3 1901.04   218.2 1894.54   287.7 1864.67   307.5 1851.25     367 1821.33
   386.9 1805.58   466.2 1760.75   538.1 1748.82   553.1 1745.97   555.6 1745.68
   565.6 1747.73   595.5 1765.72   615.5 1774.72   625.5 1780.69   635.5 1790.71
   795.2 1877.69   805.2 1886.29   875.1 1916.34     895 1929.38     945 1952.02
   964.9 1965.04   974.9 1976.39  1044.8 2019.86  1064.8  2038.8  1094.7 2057.26
#Mann= 3 , 0 , 0
       0      .1       0   538.1    .045       0   553.1      .1       0
Bank Sta=538.1,553.1
XS Rating Curve= 0 ,0
Exp/Cntr=0.3,0.1

Type RM Length L Ch R = 1 ,734     ,293.9,300,306.6
XS GIS Cut Line= 3
     1879918.302        210720.4     1880344.641      210379.298
     1880770.981      210038.196
#Sta/Elev= 30
       0 1997.51    19.8 2005.03    39.7 2007.29    59.6 2005.08    69.5 2000.96
     139 1955.63   168.8 1938.19   188.6 1923.18   208.5 1911.05   228.3 1901.97
     268 1875.31   287.9 1857.34     417  1770.2   456.6 1753.66   476.5 1743.15
   538.5 1732.42   553.5 1730.95   555.9 1730.88   565.8 1733.71   575.8 1745.07
   585.7  1752.7   655.2 1796.46   764.4 1854.31   784.2 1867.67   804.1 1877.74
     824 1882.95   943.1 1941.68     963 1948.53  1082.1 2044.66    1092 2049.68
#Mann= 3 , 0 , 0
       0      .1       0   538.5    .045       0   553.5      .1       0
Bank Sta=538.5,553.5
XS Rating Curve= 0 ,0
Exp/Cntr=0.3,0.1

Type RM Length L Ch R = 1 ,434     ,234.3,231.1,227
XS GIS Cut Line= 3
     1879986.801      210855.442     1880488.735      210639.821
     1880996.489      210439.204
#Sta/Elev= 30
       0 1905.44    59.6 1909.45    69.5 1909.42    79.5 1906.78   109.3 1909.53
   119.2 1908.87     149 1901.67   168.8 1891.45   198.6 1879.88   238.4 1861.28
   258.2 1846.47   327.8 1813.05   337.7 1803.49   347.6 1797.12   417.2  1762.2
   427.1  1751.5   456.9 1734.55   476.8 1726.75   516.5 1714.81   526.4 1713.24
   532.1 1713.24   547.1 1715.08   625.7 1734.82   754.7 1774.88   774.6 1778.56
   844.1 1785.06   873.9 1791.35   903.6 1800.19   933.4 1802.88  1092.2 1828.51
#Mann= 3 , 0 , 0
       0      .1       0   532.1    .045       0   547.1      .1       0
Bank Sta=532.1,547.1
XS Rating Curve= 0 ,0
Exp/Cntr=0.3,0.1

Type RM Length L Ch R = 1 ,202.7   ,97.7,103,108.6
XS GIS Cut Line= 3
     1880066.619      211124.043     1880544.881      210868.407
     1881024.182      210565.949
#Sta/Elev= 30
       0  1811.6    39.4 1793.18    78.9 1779.38    98.6 1770.85   157.8 1756.12
   187.3 1751.57   256.4 1753.32   305.7 1747.99   374.7  1735.1   443.7 1724.18
   463.4 1718.93   551.5 1704.59   562.2 1703.57   566.5  1703.7   582.1 1706.33
     602 1713.31   611.9 1714.92   701.4 1713.38     761 1716.76   780.9 1720.72
   820.7 1732.38   840.6 1734.34   900.2 1736.05   920.1 1738.95     940 1743.98
   999.7 1764.01  1029.5 1765.97  1049.4 1763.79  1069.3 1764.26    1109 1769.08
#Mann= 3 , 0 , 0
       0      .1       0   551.5    .045       0   566.5      .1       0
Bank Sta=551.5,566.5
XS Rating Curve= 0 ,0
Exp/Cntr=0.3,0.1

Type RM Length L Ch R = 1 ,100     ,114.8,99.9,85.1
XS GIS Cut Line= 5
     1880461.939       210935.64     1880503.223      210942.925
     1880580.933      210959.577     1880632.624      210942.231
     1880767.345      210744.429
#Sta/Elev= 30
       0 1720.06     8.4 1716.46    16.8 1714.59    33.5 1711.13    41.9 1709.49
    51.9 1707.74    61.8 1706.56    81.7 1705.35    91.6 1704.32   101.5  1703.1
   121.4 1700.14   139.6 1698.55   148.7 1698.08   157.7 1697.95   166.8 1698.82
   185.9  1702.3   195.9 1703.54   205.8 1704.56   225.8  1706.2   235.8 1706.89
   245.7 1707.21   255.7 1707.26   285.6 1708.77   315.5  1710.6   345.4 1712.85
   365.4 1713.81   385.3 1715.99   395.3 1716.98   405.3  1718.6   415.2 1721.44
#Mann= 3 , 0 , 0
       0      .1       0   148.7    .045       0   166.8      .1       0
Bank Sta=148.7,166.8
XS Rating Curve= 0 ,0
Exp/Cntr=0.3,0.1

Chan Stop Cuts=-1
Use User Specified Reach Order=0
Composite Channel Slope=5